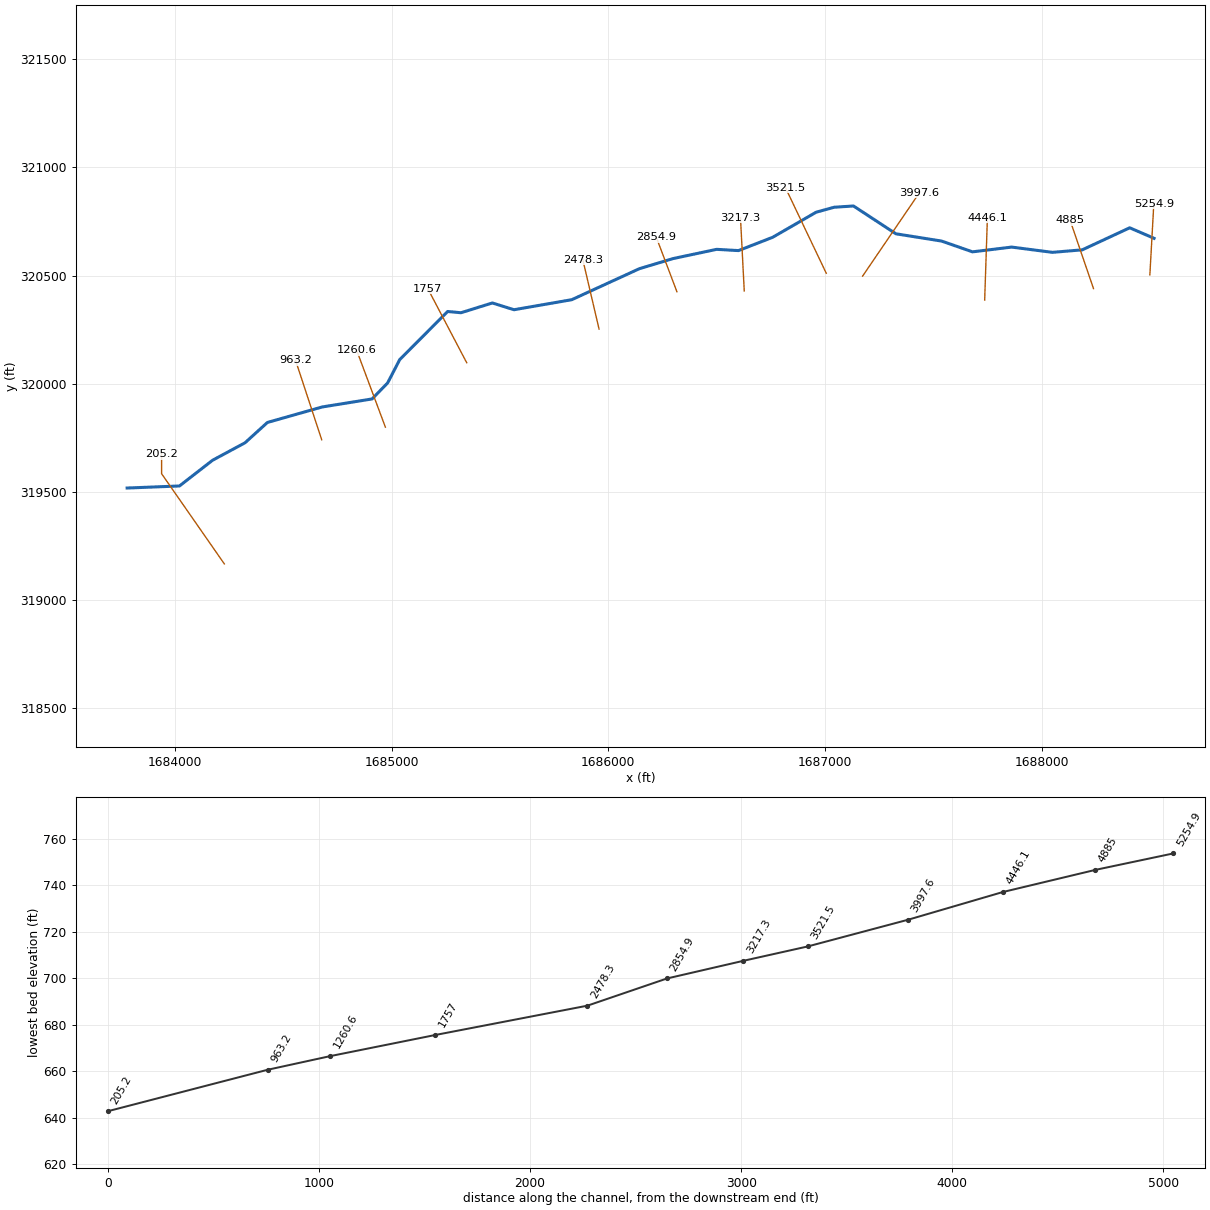
--- PEACHCRK.prj (project) ---

Proj Title=PEACHCRK
Current Plan=p01
Default Exp/Contr=0,0
English Units
Geom File=g01
Flow File=f01
Plan File=p01
BEGIN DESCRIPTION:
END DESCRIPTION:
DSS Export Rating Curves= 0
DSS Export Rating Curve Sorted= 0
DSS Export Volume Flow Curves= 0
DXF OffsetX= 0
DXF OffsetY= 0
DXF ScaleX= 0
DXF ScaleY= 0

--- PEACHCRK.p01 (plan) ---

Plan Title=Floodplain
Program Version=4.00
Geom File=g01
Flow File=f01
K Sum by GR=0
Std Step Tol=0.01
Critical Tol=0.01
Num of Std Step Trials=20
Max Error Tol=0.3
Flow Tol Ratio=0.001
Split Flow NTrial=30
Split Flow Tol=0.02
Split Flow Ratio=0.02
Log Output Level=0
Friction Slope Method=1
Unsteady Friction Slope Method=2
Unsteady Bridges Friction Slope Method=1
Global Log Level=0
CheckData=False
Run HTab=0
Run UNet=0
Run PostProcess=0
UNET Theta=0
UNET Theta Warmup=0
UNET ZTol=0
UNET ZSATol=0
UNET MxIter=0
UNET MaxInSteps=0
UNET DtIC=0
UNET DtMin=0
UNET MaxCRTS=0
UNET WFStab=0
UNET SFStab=0
UNET WFX=0
UNET SFX=0
UNET DSS MLevel=0
UNET DZMax Abort=0
UNET Convert EG Bridges=0
UNET Use Existing IB Tables=0
UNET Froude Limit=0
UNET Froude Power=0
Write IC File=0
Echo Input=False
Echo Output=False
Write Detailed=0

--- PEACHCRK.f01 (steady flow) ---

Flow Title=NFF Regression Equation
Program Version=4.00
Number of Profiles=1
Profile Names=P100yr
River Rch & RM=PEACHCRK,Main      ,5254.9
900.6290
River Rch & RM=PEACHCRK,Main      ,3521.5
950.5514
River Rch & RM=PEACHCRK,Main      ,205.2
1024.549
Boundary for River Rch & Prof#=PEACHCRK,Main      ,1
Up Type=0
Dn Type=3
Dn Slope=0.020527

--- PEACHCRK.g01 (geometry) ---

Geom Title=USGS 10m DEM
Program Version=4.10

River Reach=PEACHCRK        ,Main
Reach XY= 30
     1688517.849      320672.139     1688405.479      320720.794
     1688186.532       320618.85     1688048.676      320607.266
     1687861.007      320631.593     1687680.289      320609.583
       1687537.8      320659.396     1687326.962      320692.991
     1687131.184      320821.579     1687041.983      320815.786
     1686958.575      320792.618     1686758.163      320676.773
     1686600.614      320615.375     1686499.829      320621.167
     1686298.259      320578.304     1686144.185      320531.967
     1685831.403      320388.319      1685564.96      320341.981
     1685465.333      320373.259     1685320.527      320328.079
     1685259.129      320333.871     1685037.865      320111.449
     1684982.259      320003.713     1684910.435      319929.572
     1684680.131      319892.437      1684427.58      319820.857
      1684324.26      319726.844     1684174.802      319646.258
     1684021.919      319527.253     1683780.434      319517.698

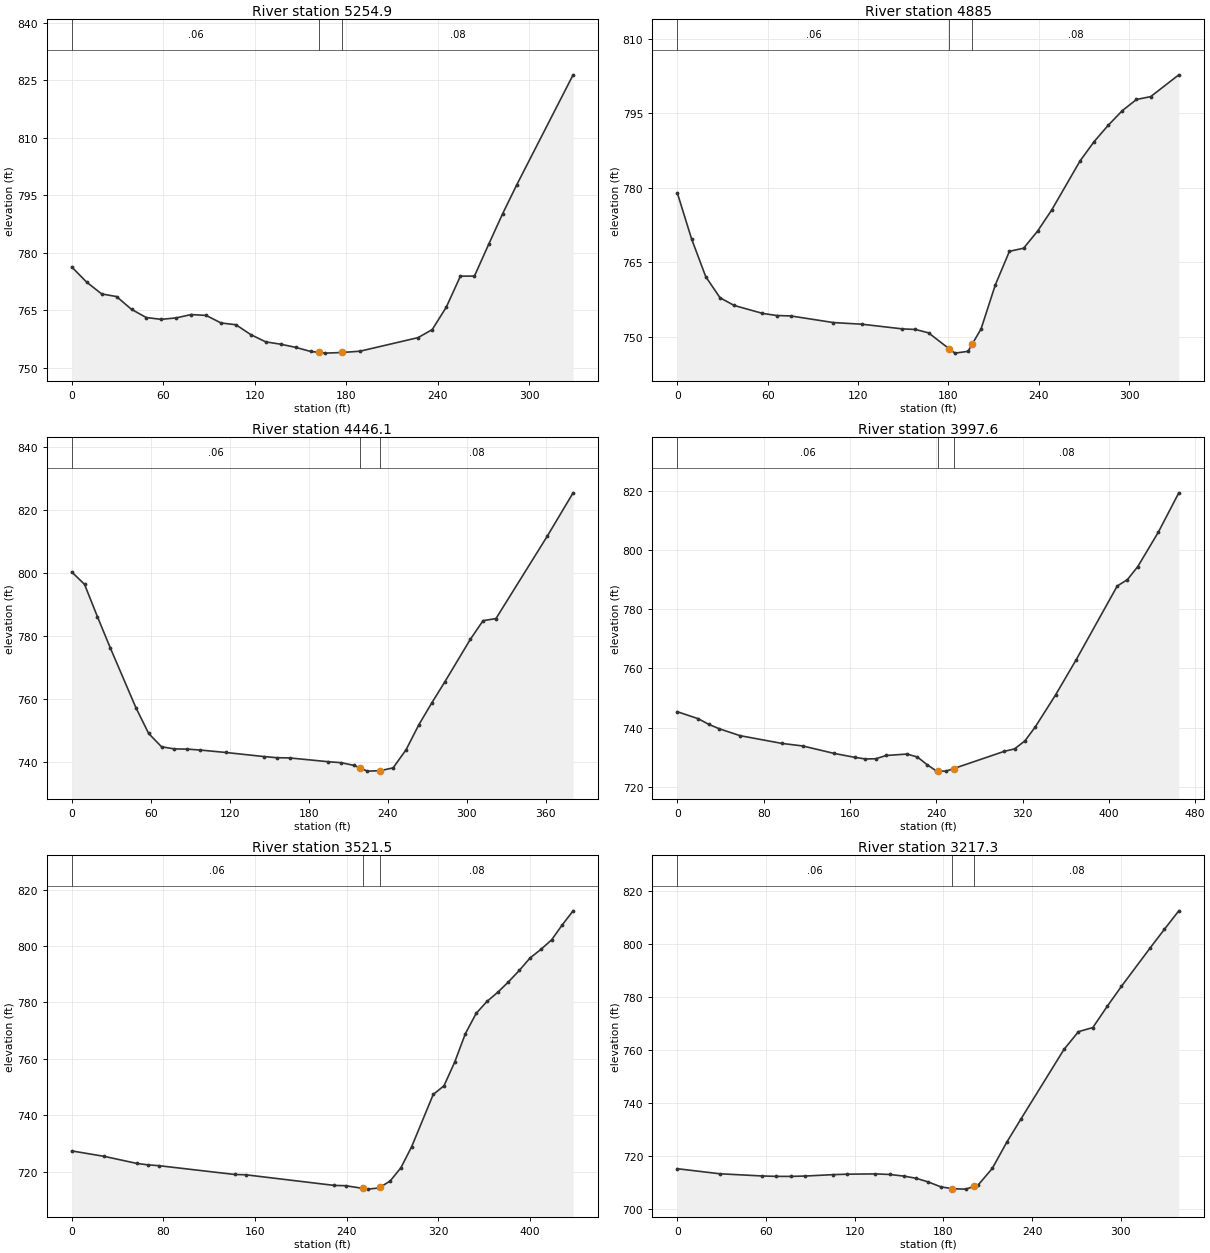
Type RM Length L Ch R = 1 ,5254.9  ,361.1,369.9,378.7
XS GIS Cut Line= 5
     1688498.445      320503.161     1688507.676      320669.302
     1688507.864      320672.694     1688510.531      320720.703
     1688516.687      320831.505
#Sta/Elev= 30
       0  776.27     9.8   772.3    19.6  769.24    29.4  768.54    39.2  765.21
    48.9  763.07    58.7   762.6    68.5  762.98    78.3  763.85    88.1  763.63
    97.9  761.66   107.7  761.19   117.5   758.6   127.2  756.73     137  756.12
   146.8   755.3   156.6  754.23   162.3  753.97   166.4  753.79   177.3  753.96
     189  754.29   227.1  757.83   236.4  759.93   245.6  765.76   254.9  773.87
   264.1  773.89   273.4  782.15   282.6  790.17   291.9  797.74   328.8  826.38
#Mann= 3 , 0 , 0
       0     .06       0   162.3    .045       0   177.3     .08       0
Bank Sta=162.3,177.3
XS Rating Curve= 0 ,0
Exp/Cntr=0.3,0.1

Type RM Length L Ch R = 1 ,4885    ,446.6,438.4,430.2
XS GIS Cut Line= 4
     1688238.502       320439.58     1688195.822       320564.37
     1688173.216      320630.469     1688130.732      320754.688
#Sta/Elev= 30
       0  778.87     9.4  769.68    18.8  762.09    28.3  757.84    37.7  756.29
    56.5   754.7    65.9  754.27    75.4  754.18   103.6  752.85   122.5  752.52
   149.4  751.58   158.1  751.46   166.8  750.78   180.7  747.52   184.3   746.7
     193  747.06   195.7  748.47   201.7   751.6   211.1   760.4   220.5  767.19
   229.9  767.81   239.2  771.25   248.6  775.51   267.4  785.37   276.8  789.28
   286.1  792.54   295.5   795.5   304.9  797.74   314.3  798.31     333   802.7
#Mann= 3 , 0 , 0
       0     .06       0   180.7    .045       0   195.7     .08       0
Bank Sta=180.7,195.7
XS Rating Curve= 0 ,0
Exp/Cntr=0.3,0.1

Type RM Length L Ch R = 1 ,4446.1  ,461.4,448.5,435.5
XS GIS Cut Line= 4
     1687736.409      320386.782     1687741.869      320552.224
     1687744.462      320630.758      1687748.97      320767.356
#Sta/Elev= 30
       0  800.37     9.7  796.47    19.5   786.2    29.2  776.36    48.7  757.35
    58.4  749.13    68.2   744.9    77.9  744.22    87.6  744.16    97.4  743.87
   116.8   743.1   146.1  741.79   155.8  741.43   165.5  741.36     195  740.15
   204.8  739.84   214.6  738.96   219.2  738.13   224.5  737.17   234.2   737.3
   244.1  738.21   253.9  743.93   263.6  751.87   273.4  758.78   283.2  765.39
   302.7  778.97   312.4  784.92   322.2  785.58   361.3  811.82   380.8  825.49
#Mann= 3 , 0 , 0
       0     .06       0   219.2    .045       0   234.2     .08       0
Bank Sta=219.2,234.2
XS Rating Curve= 0 ,0
Exp/Cntr=0.3,0.1

Type RM Length L Ch R = 1 ,3997.6  ,452.1,475.8,499.4
XS GIS Cut Line= 4
     1687173.384      320497.562     1687298.566      320681.668
     1687333.115      320732.479     1687434.792      320882.016
#Sta/Elev= 30
       0  745.32    19.4  742.96      29  741.08    38.7  739.59    58.1  737.24
    96.8  734.63   116.2  733.76   145.2  731.25   164.6  729.91   174.2  729.37
   183.9  729.44   193.6  730.55     213  731.03   222.6  730.01   231.4  727.47
   240.2   725.3   241.3   725.3     249  725.26   256.3  726.14   303.1  731.95
   312.6  732.78   322.2  735.48   331.7  740.14   350.7  751.05   369.7  762.87
   407.8   787.8   417.3  789.99   426.8  794.34   445.9  805.99   464.9  819.29
#Mann= 3 , 0 , 0
       0     .06       0   241.3    .045       0   256.3     .08       0
Bank Sta=241.3,256.3
XS Rating Curve= 0 ,0
Exp/Cntr=0.3,0.1

Type RM Length L Ch R = 1 ,3521.5  ,313.3,304.3,295.2
XS GIS Cut Line= 4
     1687005.631       320510.53     1686940.473      320647.512
     1686886.275      320761.449     1686817.639      320905.742
#Sta/Elev= 30
       0  727.32    28.4  725.38    56.9  722.87    66.4  722.38    75.8  722.09
   142.2  718.96   151.7  718.86   229.3  715.07     239  714.98   253.9  714.03
   258.4  713.76   268.2  714.18   268.9  714.36   277.9  716.64   287.3  721.34
   296.7  728.83   315.5  747.34   324.9  750.42   334.2  758.78   343.6  768.95
     353  776.12   362.4  780.35   371.8  783.59   381.2   787.3   390.6  791.34
     400  795.76   409.4  798.79   418.8  802.18   428.2  807.56   437.6   812.5
#Mann= 3 , 0 , 0
       0     .06       0   253.9    .045       0   268.9     .08       0
Bank Sta=253.9,268.9
XS Rating Curve= 0 ,0
Exp/Cntr=0.3,0.1

Type RM Length L Ch R = 1 ,3217.3  ,355.2,362.2,369.2
XS GIS Cut Line= 4
     1686627.279      320428.946     1686619.415      320581.915
     1686616.835       320632.12     1686609.861      320767.771
#Sta/Elev= 30
       0  715.27    28.7  713.37    57.4  712.54      67  712.39    76.6  712.38
    86.2  712.51   105.3  713.04   114.9  713.21     134  713.32   143.6  713.11
   153.2   712.5   161.6  711.67   169.9  710.26   178.3  708.44   185.8  707.79
   186.7  707.71   195.1  707.59   200.8  708.61   203.4  709.07   213.1  715.41
   222.8  725.18   232.6  734.11   261.6  760.19   271.4  766.87   281.1   768.4
   290.8  776.36   300.5  783.94   319.9  798.37   329.6  805.44   339.3  812.35
#Mann= 3 , 0 , 0
       0     .06       0   185.8    .045       0   200.8     .08       0
Bank Sta=185.8,200.8
XS Rating Curve= 0 ,0
Exp/Cntr=0.3,0.1

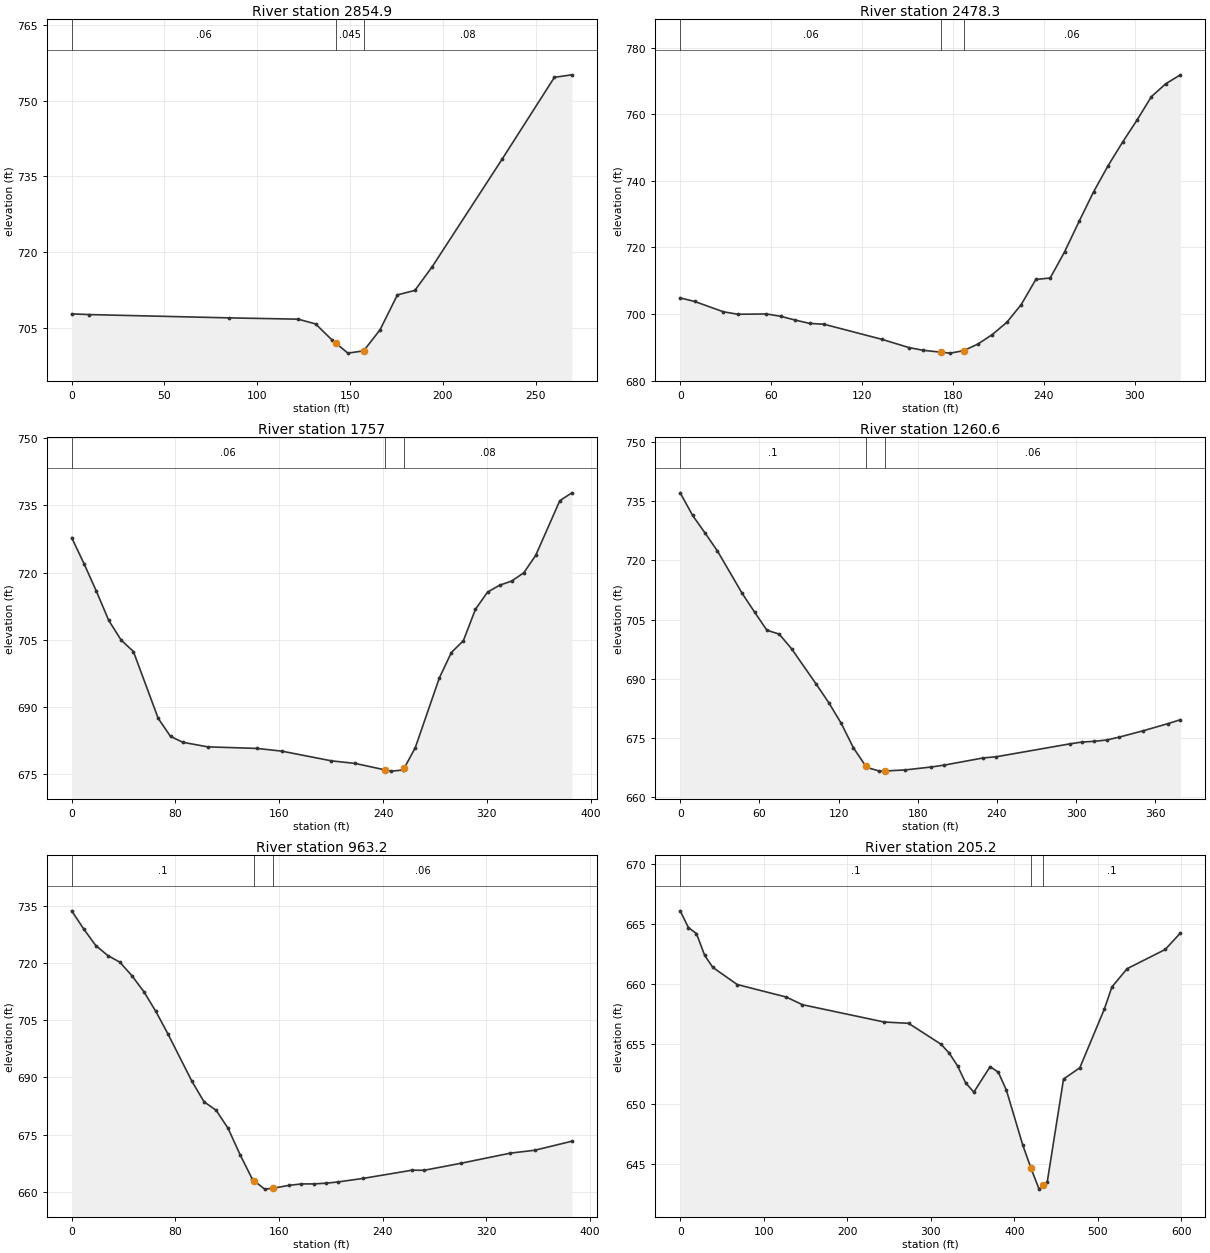
Type RM Length L Ch R = 1 ,2854.9  ,379.5,376.6,373.6
XS GIS Cut Line= 4
      1686316.61      320425.171      1686270.21      320548.132
     1686257.959      320580.597     1686221.454      320677.336
#Sta/Elev= 16
       0  707.76     9.4  707.62    84.5  706.97     122  706.71   131.4  705.77
   140.1  702.65   142.3  701.97   148.8  699.98   157.3  700.43   166.1  704.58
   175.5  711.52   184.9  712.41   194.3  717.13   231.9  738.41   260.1  754.64
   269.5  755.13
#Mann= 3 , 0 , 0
       0     .06       0   142.3    .045       0   157.3     .08       0
Bank Sta=142.3,157.3
XS Rating Curve= 0 ,0
Exp/Cntr=0.3,0.1

Type RM Length L Ch R = 1 ,2478.3  ,715.3,720.9,726.5
XS GIS Cut Line= 4
     1685957.494      320252.511     1685927.271      320381.893
      1685912.82      320443.756      1685882.43      320573.852
#Sta/Elev= 30
       0  704.86     9.5   703.8    28.5   700.7      38  699.96    56.9  700.04
    66.4  699.34    75.9   698.2    85.4  697.21    94.9  696.96   132.9  692.45
     151  689.95   160.1  689.15   171.9  688.58   178.2  688.29   186.9  689.02
   196.4  691.01   205.9  693.87   215.5  697.54     225  702.88   234.6  710.39
   244.1  710.84   253.6   718.7   263.2  727.87   272.7  736.69   282.3  744.55
   291.8  751.58   301.4  758.26   310.9  765.29   320.4  769.16     330  771.82
#Mann= 3 , 0 , 0
       0     .06       0   171.9    .045       0   186.9     .06       0
Bank Sta=171.9,186.9
XS Rating Curve= 0 ,0
Exp/Cntr=0.3,0.1

Type RM Length L Ch R = 1 ,1757    ,499.3,496.2,493
XS GIS Cut Line= 4
     1685346.966      320096.867     1685254.109      320274.072
     1685228.373      320323.185     1685168.034      320438.334
#Sta/Elev= 30
       0  727.79     9.5     722      19  715.86    28.6   709.3    38.1  704.94
    47.6  702.36    66.7  687.44    76.2  683.41    85.7  682.11   104.8  681.09
   142.9  680.74     162  680.13   200.1  677.97   218.5  677.39   241.4  675.95
   246.3  675.67   255.5  675.92   256.4   676.4   264.8   680.9   283.4  696.51
   292.6  702.14   301.9  704.81   311.2  711.81   320.5  715.64   329.8  717.17
   339.1  718.11   348.4  719.94   357.6  723.82   376.2  736.05   385.5   737.8
#Mann= 3 , 0 , 0
       0     .06       0   241.4    .045       0   256.4     .08       0
Bank Sta=241.4,256.4
XS Rating Curve= 0 ,0
Exp/Cntr=0.3,0.1

Type RM Length L Ch R = 1 ,1260.6  ,298,297.3,296.7
XS GIS Cut Line= 4
     1684971.813       319799.04     1684925.919      319922.106
     1684888.171      320023.327     1684839.397      320154.114
#Sta/Elev= 30
       0  737.15     9.4  731.42    18.8  726.98    28.2  722.42    46.9   711.7
    56.3  706.94    65.7  702.32      75  701.34    84.4  697.63   103.2  688.59
   112.6  683.95     122  678.72   131.3  672.49   140.4  667.98   141.2  667.58
     151  666.61   155.4  666.65   170.6  666.92   190.3  667.66   200.1  668.14
   229.6  669.96   239.4  670.25   295.2  673.52   304.5  673.98   313.8  674.17
   323.1   674.5   332.4  675.21     351  676.86   369.6  678.65     379  679.64
#Mann= 3 , 0 , 0
       0      .1       0   140.4    .045       0   155.4     .06       0
Bank Sta=140.4,155.4
XS Rating Curve= 0 ,0
Exp/Cntr=0.3,0.1

Type RM Length L Ch R = 1 ,963.2   ,749.7,757.3,764.8
XS GIS Cut Line= 4
     1684678.067      319740.694     1684637.479      319864.295
     1684599.077      319981.241     1684557.591      320107.575
#Sta/Elev= 30
       0  733.66     9.3   728.9    18.6  724.56    27.9  721.94    37.2  720.21
    46.5  716.66    55.8  712.44      65  707.29    74.3  701.42    92.9  688.95
   102.2  683.61   111.5   681.4   120.8  676.63   130.1  669.69   139.6  663.26
   140.7  662.96     149  660.72   155.7  660.97     168  661.72   177.4  662.08
   186.9  662.09   196.4  662.27   205.8  662.61   224.8  663.52   262.7  665.68
   272.2  665.66   300.7  667.51   338.7  670.15   357.7  670.92   386.2  673.28
#Mann= 3 , 0 , 0
       0      .1       0   140.7    .045       0   155.7     .06       0
Bank Sta=140.7,155.7
XS Rating Curve= 0 ,0
Exp/Cntr=0.3,0.1

Type RM Length L Ch R = 1 ,205.2   ,221,205.2,189.5
XS GIS Cut Line= 3
     1684228.883      319166.845     1683939.369      319583.908
     1683939.281       319675.02
#Sta/Elev= 30
       0  666.06     9.8  664.67    19.5  664.16    29.3  662.35      39  661.35
    68.3  659.92   126.9  658.88   146.4  658.24   244.1   656.8   273.4  656.69
   312.4  654.94   322.2  654.19     332  653.15   341.7  651.73   351.5  650.96
     371  653.08   380.8  652.62   390.5  651.12   410.1  646.55   419.9  644.63
   429.6  642.88   434.9   643.2   439.4  643.48   458.9  652.05   478.4  652.99
   507.7  657.87   516.8  659.72     535  661.24   580.6  662.84   598.8  664.21
#Mann= 3 , 0 , 0
       0      .1       0   419.9    .045       0   434.9      .1       0
Bank Sta=419.9,434.9
XS Rating Curve= 0 ,0
Exp/Cntr=0.3,0.1

Chan Stop Cuts=-1
Use User Specified Reach Order=0
Composite Channel Slope=5